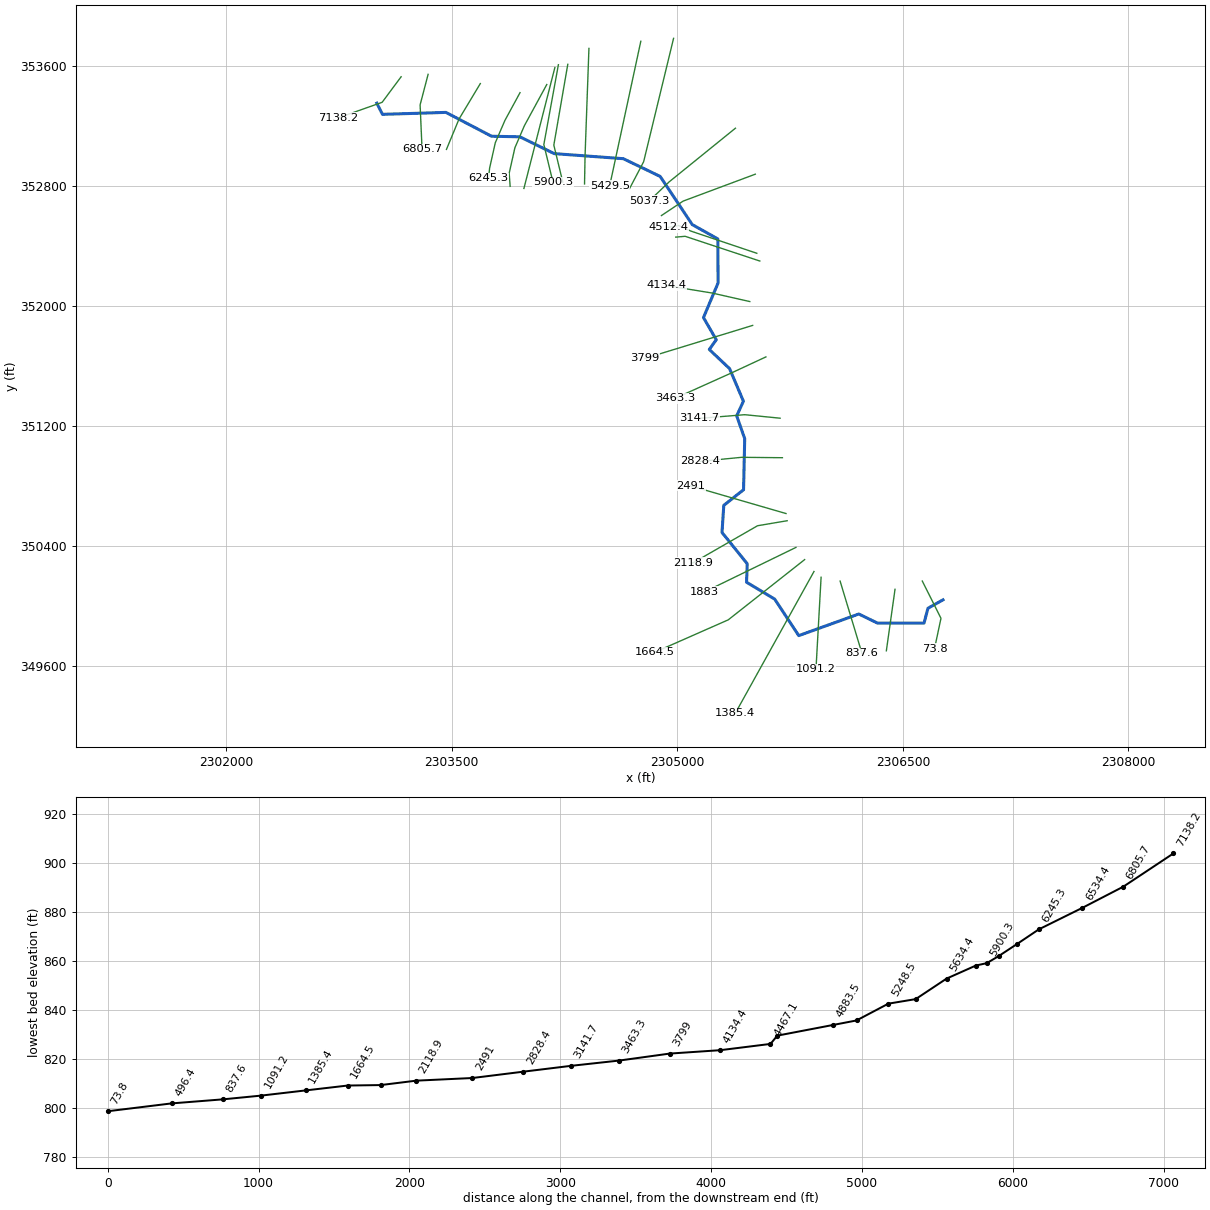
--- BREAKNECKR.prj (project) ---

Proj Title=BREAKNECKR
Current Plan=p01
Default Exp/Contr=0,0
English Units
Geom File=g01
Flow File=f01
Plan File=p01
BEGIN DESCRIPTION:
END DESCRIPTION:
DSS Export Rating Curves= 0
DSS Export Rating Curve Sorted= 0
DSS Export Volume Flow Curves= 0
DXF OffsetX= 0
DXF OffsetY= 0
DXF ScaleX= 0
DXF ScaleY= 0

--- BREAKNECKR.p01 (plan) ---

Plan Title=Floodplain
Program Version=4.00
Geom File=g01
Flow File=f01
K Sum by GR=0
Std Step Tol=0.01
Critical Tol=0.01
Num of Std Step Trials=20
Max Error Tol=0.3
Flow Tol Ratio=0.001
Split Flow NTrial=30
Split Flow Tol=0.02
Split Flow Ratio=0.02
Log Output Level=0
Friction Slope Method=1
Unsteady Friction Slope Method=2
Unsteady Bridges Friction Slope Method=1
Global Log Level=0
CheckData=False
Run HTab=0
Run UNet=0
Run PostProcess=0
UNET Theta=0
UNET Theta Warmup=0
UNET ZTol=0
UNET ZSATol=0
UNET MxIter=0
UNET MaxInSteps=0
UNET DtIC=0
UNET DtMin=0
UNET MaxCRTS=0
UNET WFStab=0
UNET SFStab=0
UNET WFX=0
UNET SFX=0
UNET DSS MLevel=0
UNET DZMax Abort=0
UNET Convert EG Bridges=0
UNET Use Existing IB Tables=0
UNET Froude Limit=0
UNET Froude Power=0
Write IC File=0
Echo Input=False
Echo Output=False
Write Detailed=0

--- BREAKNECKR.f01 (steady flow) ---

Flow Title=NFF Regression Equation
Program Version=4.10
Number of Profiles= 1
Profile Names=P100yr
River Rch & RM=BREAKNECKR,Main            ,7138.2
400.5324
River Rch & RM=BREAKNECKR,Main            ,6534.4
 689.484
River Rch & RM=BREAKNECKR,Main            ,4883.5
710.9332
River Rch & RM=BREAKNECKR,Main            ,1664.5
785.7346
River Rch & RM=BREAKNECKR,Main            ,1385.4
1033.165
River Rch & RM=BREAKNECKR,Main            ,837.6
1036.613
River Rch & RM=BREAKNECKR,Main            ,496.4
1038.757
Boundary for River Rch & Prof#=BREAKNECKR,Main            , 1
Up Type= 0
Dn Type= 3
Dn Slope=0.006
DSS Import GetInterval= 0
DSS Import GetPeak= 0
DSS Import FillOption= 0

--- BREAKNECKR.g01 (geometry) ---

Geom Title=USGS 10m DEM
Program Version=4.10

River Reach=BREAKNECKR      ,Main
Reach XY= 30
2303001.34250842353351.2632277612303039.10293159353277.044544175
2303460.97807209353290.0651874242303764.36362018353131.211174428
2303953.16540793353127.3046861742304181.03010967 353015.32557942
2304641.09972759352981.4713164272304885.89123276 352863.41577825
2305099.43280043352542.2353182582305269.57189584352446.749288753
2305271.30778477352153.3463322522305174.08553825351922.443578839
2305259.15525001351774.8743201792305212.67371568351710.030617833
 2305347.6967396351582.1660441762305439.70738234351365.157619923
2305395.12446626 351267.20670034  2305448.391092351115.151886344
2305440.69753784350775.0190364272305309.18697409350670.852578089
2305297.34972742350490.1521520912305465.34151742350281.361559168
2305460.54395485350158.5547181672305648.04390793350045.707502916
2305807.76635751349802.6518866722306207.07166126349946.749367505
2306332.07173935349885.985381424 2306641.0996646349885.985381424
2306667.14127918349984.9438449292306767.12729968350041.077262834

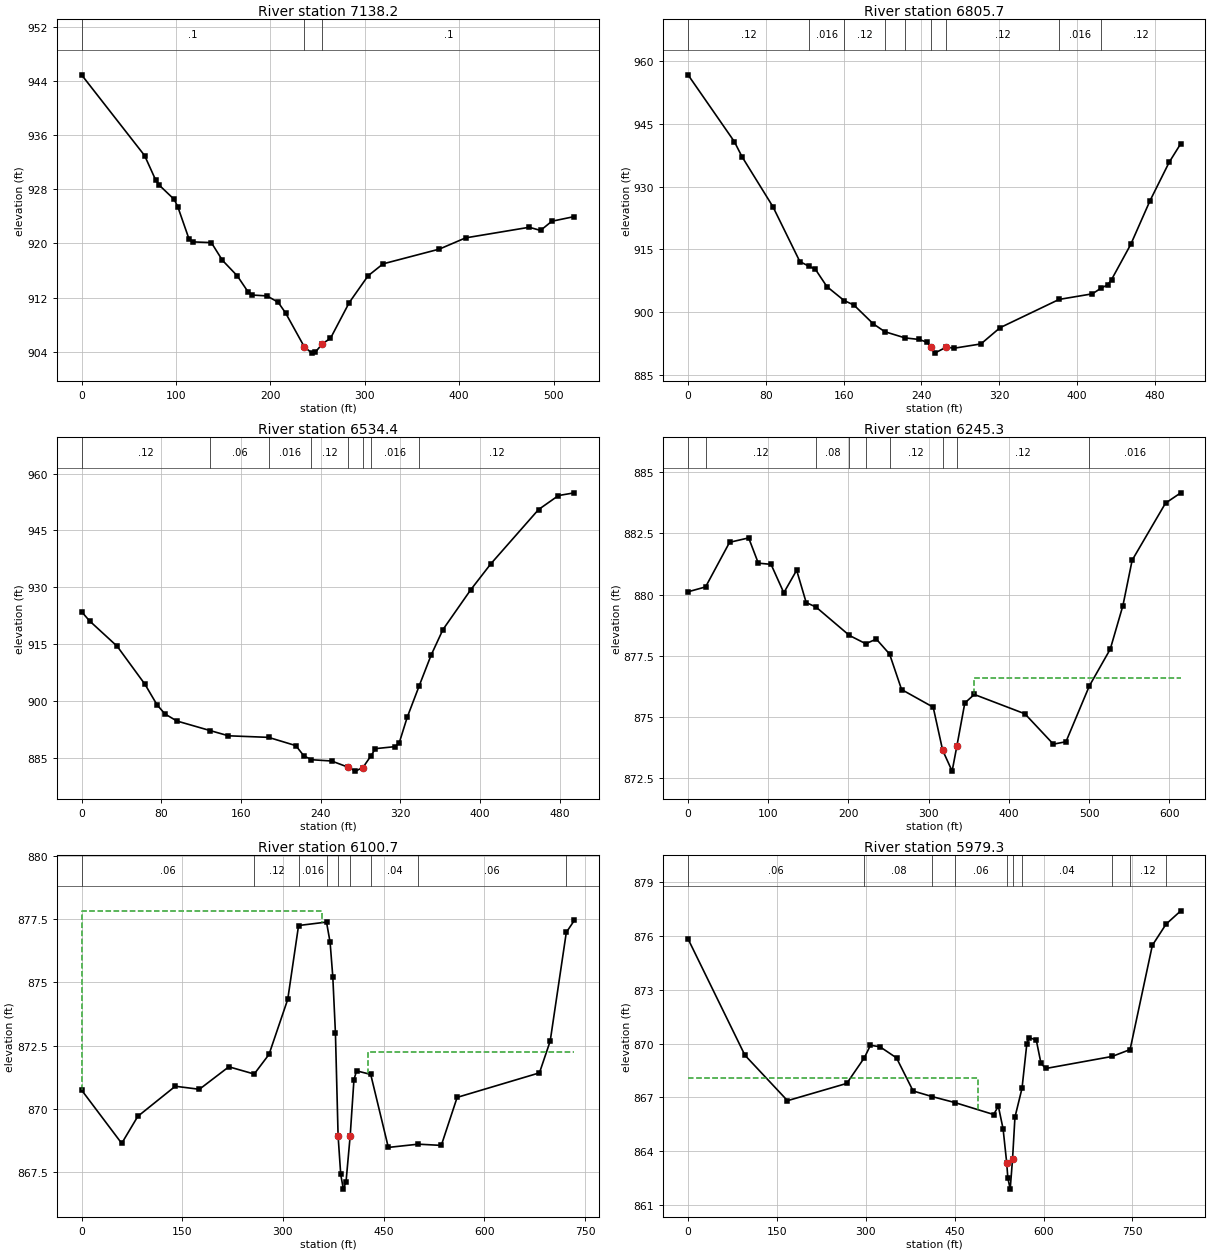
Type RM Length L Ch R = 1 ,7138.2  ,283.9,332.5,382.5
XS GIS Cut Line= 3
     2303163.185      353527.609     2303036.835      353357.267
     2302744.746      353253.696
#Sta/Elev= 30
       0  944.94    66.8     933    78.6  929.36    82.5   928.6    98.2  926.51
   102.1  925.37   113.9  920.64   117.8  920.24   137.5  920.13   149.2  917.52
     165  915.21   176.7  912.78   180.7  912.38   196.4  912.25   208.2  911.32
   216.1  909.74   235.9  904.74   243.9  903.79   247.8  903.96   255.1  905.17
   263.7  905.98   283.6  911.27   303.5  915.22   319.4  916.99     379  919.17
   406.8  920.83   474.3   922.4   486.2  921.93   498.2  923.29     522  923.98
#Mann= 3 , 0 , 0
       0      .1       0   235.9    .045       0   255.1      .1       0
Bank Sta=235.9,255.1
XS Rating Curve= 0 ,0
Exp/Cntr=0.3,0.1

Type RM Length L Ch R = 1 ,6805.7  ,293.1,271.3,254.6
XS GIS Cut Line= 3
     2303342.653      353543.764     2303289.439       353340.34
     2303302.313      353044.233
#Sta/Elev= 30
       0  956.72    47.6  940.77    55.5  937.16    87.3  925.21     115   912.1
  124.63910.9426   130.9  910.28   142.8  906.12   160.5 902.787   170.6  901.71
   190.4  897.23  202.38895.3404  223.18893.8565   237.9  893.48   245.8   892.8
   249.8  891.64   253.7  890.22   265.6  891.66   273.5  891.39   301.2  892.42
   320.9   896.3  381.54903.0504   415.8  904.39  424.29 905.682   431.6  906.56
   435.5  907.79   455.3  916.22     475  926.61   494.8  935.84   506.7  940.28
#Mann= 9 ,-1 , 0
       0     .12       0  124.63    .016       0   160.5     .12       0
  202.38     .08       0  223.18     .12       0   249.8    .045       0
   265.6     .12       0  381.54    .016       0  424.29     .12       0
Bank Sta=249.8,265.6
XS Rating Curve= 0 ,0
Exp/Cntr=0.3,0.1

Type RM Length L Ch R = 1 ,6534.4  ,285,289,288
XS GIS Cut Line= 3
     2303689.873      353482.034     2303548.497      353246.408
     2303464.597      353043.399
#Sta/Elev= 30
       0  923.61       8  921.18    35.8  914.47    63.7  904.44    75.7  899.08
    83.6  896.67    95.6   894.8  129.04892.2729   147.4   890.9  187.63890.4853
     215  888.31     223  885.62  230.69884.5924   250.9  884.26   267.3  882.64
   274.8  881.59   282.3  882.54  290.41885.6271   294.8  887.51   314.7  888.05
   318.7  889.01   326.7  895.74  338.79904.0829   350.7  912.14   362.6  918.89
   390.6  929.42   410.6   936.2   458.5  950.51   478.5   954.2   494.4  954.92
#Mann= 8 ,-1 , 0
       0     .12       0  129.04     .06       0  187.63    .016       0
  230.69     .12       0   267.3    .045       0   282.3     .12       0
  290.41    .016       0  338.79     .12       0
Bank Sta=267.3,282.3
XS Rating Curve= 0 ,0
Exp/Cntr=0.3,0.1

Type RM Length L Ch R = 1 ,6245.3  ,143.6,144.6,144.7
XS GIS Cut Line= 5
     2303953.917      353421.629     2303853.241      353236.174
     2303789.439      353087.736     2303751.678      352918.465
     2303744.285      352850.695
#Sta/Elev= 30
       0  880.12   21.89880.3195    51.8  882.14    75.6  882.32    87.6  881.29
   103.5  881.24   119.4  880.08   135.4     881   147.3  879.68  159.48879.4995
   201.1  878.34  221.54     878   234.7  878.19  251.23877.5783   266.2  876.13
   305.6  875.41   317.4  873.65   329.2   872.8   335.1  873.82     345  875.58
   356.8  875.93   419.9  875.14   455.4   873.9   471.1     874  500.21876.2755
   526.3  877.78   542.1  879.56   553.6  881.41   595.2  883.74   614.2  884.16
#Mann= 9 ,-1 , 0
       0     .08       0   21.89     .12       0  159.48     .08       0
   201.1     .12       0  221.54    .016       0  251.23     .12       0
   317.4    .045       0   335.1     .12       0  500.21    .016       0
#XS Ineff= 2 , 0
                          356.96          876.62
Permanent Ineff=
       F       F
Bank Sta=317.4,335.1
XS Rating Curve= 0 ,0
Exp/Cntr=0.3,0.1

Type RM Length L Ch R = 1 ,6100.7  ,115.1,121.5,127.6
XS GIS Cut Line= 5
     2304131.887      353475.757     2303983.449       353202.32
     2303919.647      353053.882     2303881.887      352884.611
     2303888.139      352797.076
#Sta/Elev= 30
       0  870.74    59.8  868.63    83.8   869.7   139.6  870.89   175.5  870.77
   219.4  871.66  257.15871.3731   279.2  872.15   307.1  874.33  323.21877.2486
  364.84877.3848   370.2  876.58   374.2  875.22   378.1  873.01   382.1  868.92
     386   867.4   389.9  866.82   393.9  867.11   400.1  868.93   405.7  871.15
   409.6   871.5  430.68871.3576   456.9  868.47   501.5868.5985   535.8  868.55
   559.4  870.45     682  871.42     698  872.68  721.98 876.977   733.9  877.45
#Mann= 9 ,-1 , 0
       0     .06       0  257.15     .12       0  323.21    .016       0
  364.84     .12       0   382.1    .045       0   400.1     .12       0
  430.68     .04       0   501.5     .06       0  721.98    .016       0
#XS Ineff= 2 , 0
          357.95  877.83  426.14          872.24
Permanent Ineff=
       F       F
Bank Sta=382.1,400.1
XS Rating Curve= 0 ,0
Exp/Cntr=0.3,0.1

Type RM Length L Ch R = 1 ,5979.3  ,56.5,79,100.7
XS GIS Cut Line= 2
     2304185.706      353589.038     2303979.837      352783.196
#Sta/Elev= 30
       0  875.82      96  869.35   167.9  866.82   267.9  867.78  297.69869.2116
   307.9   869.9   323.9  869.82   351.9   869.2   379.9  867.36  412.39867.0436
  450.59866.7133   515.8  866.05   523.8  866.51   531.8  865.25   537.9  863.36
   539.8  862.52   543.8   861.9   547.8   863.6   551.8   865.9  563.75867.5107
   571.8  869.97   575.8  870.33   587.8  870.19   595.8  868.89   603.8  868.61
  715.81869.2802  746.15869.6629   783.7  875.46  806.83876.6382   831.7  877.38
#Mann= 10 ,-1 , 0
       0     .06       0  297.69     .08       0  412.39    .016       0
  450.59     .06       0   537.9    .045       0   547.8     .06       0
  563.75     .04       0  715.81     .08       0  746.15     .12       0
  806.83     .06       0
#XS Ineff= 2 , 0
          490.06  868.09
Permanent Ineff=
       F       F
Bank Sta=537.9,547.8
XS Rating Curve= 0 ,0
Exp/Cntr=0.3,0.1

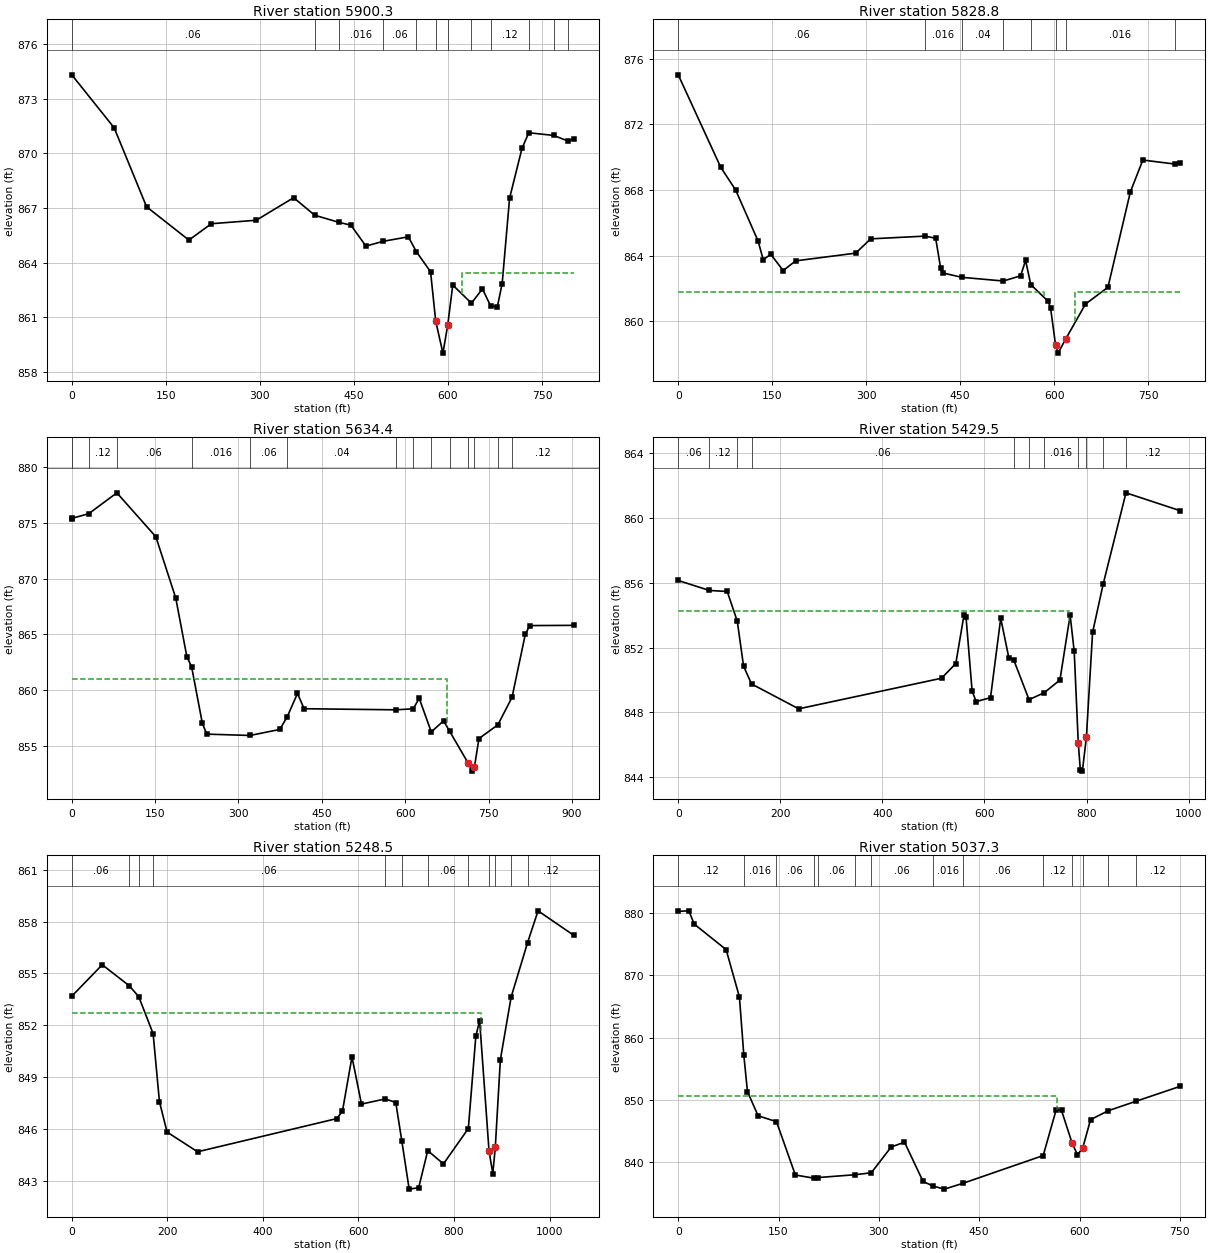
Type RM Length L Ch R = 1 ,5900.3  ,75.4,71.5,68.5
XS GIS Cut Line= 3
     2304209.144      353607.919     2304112.355      353076.017
     2304173.445      352823.231
#Sta/Elev= 30
       0  874.32    67.6  871.41   119.3  867.07   186.8  865.24   222.6  866.14
   294.2  866.33   353.8  867.57   387.5 866.605  426.14866.2148   445.2  866.06
   469.1  864.91  496.44865.1723   536.7  865.42  549.66864.5981   572.2   863.5
   580.4  860.79   591.9  859.03   599.7   860.6   607.6  862.77  637.39861.7751
   654.9  862.56  667.88861.6309   678.6  861.56   686.4  862.85   698.2  867.54
     718  870.28  728.87871.1372  768.45870.9912  791.69870.6757   800.7   870.8
#Mann= 12 ,-1 , 0
       0     .06       0   387.5     .08       0  426.14    .016       0
  496.44     .06       0  549.66    .016       0   580.4    .045       0
   599.7    .016       0  637.39     .04       0  667.88     .12       0
  728.87     .08       0  768.45     .06       0  791.69     .08       0
#XS Ineff= 2 , 0
                          622.16          863.41
Permanent Ineff=
       F       F
Bank Sta=580.4,599.7
XS Rating Curve= 0 ,0
Exp/Cntr=0.3,0.1

Type RM Length L Ch R = 1 ,5828.8  ,205.2,194.5,184.5
XS GIS Cut Line= 3
     2304271.643      353610.523     2304178.762      353072.111
     2304238.615      352824.441
#Sta/Elev= 30
       0  875.02    67.8  869.39    91.7     868   127.6  864.88   135.6  863.76
   147.6  864.09   167.5   863.1   187.4  863.69   283.2  864.16   307.1  865.03
  393.51865.1961   410.8  865.07   418.8  863.23   422.7  862.95  452.41862.6874
  518.82862.4621   546.4  862.78   554.3  863.72  562.55862.2438   590.2  861.23
   594.1  860.84   602.1  858.57   606.1  858.07     618  858.91   649.9  861.06
   685.7  862.08   721.5  867.89   741.4  869.83  793.36869.5816   801.2  869.68
#Mann= 8 ,-1 , 0
       0     .06       0  393.51    .016       0  452.41     .04       0
  518.82     .08       0  562.55     .06       0   602.1    .045       0
     618    .016       0  793.36     .12       0
#XS Ineff= 2 , 0
          583.81  861.81  633.52          861.81
Permanent Ineff=
       F       F
Bank Sta=602.1,618
XS Rating Curve= 0 ,0
Exp/Cntr=0.3,0.1

Type RM Length L Ch R = 1 ,5634.4  ,211.3,204.8,197.4
XS GIS Cut Line= 3
     2304412.268      353716.425     2304386.476      353000.011
     2304383.018      352813.285
#Sta/Elev= 30
       0  875.34       1875.4325   30.52875.8365   81.16877.7112   151.3  873.77
   187.2  868.26   207.1  863.01  215.66862.1068     235  857.03   242.9  856.06
  320.82855.9399   374.4  856.48  387.91857.6343   406.2  859.71   418.2  858.34
  583.52858.2404  614.58858.3344   625.3  859.27  647.02856.2581   669.1  857.25
  680.05856.3177   712.9   853.5   720.8  852.74   724.8  853.15   732.8  855.66
  766.84856.8965  792.32859.3558   816.2  865.01   824.2   865.8   903.6  865.82
#Mann= 15 ,-1 , 0
       0     .12       0       1     .06       0   30.52     .12       0
   81.16     .06       0  215.66    .016       0  320.82     .06       0
  387.91     .04       0  583.52     .06       0  614.58     .04       0
  647.02     .06       0  680.05     .12       0   712.9    .045       0
   724.8     .12       0  766.84    .016       0  792.32     .12       0
#XS Ineff= 2 , 0
          674.72  860.97
Permanent Ineff=
       F       F
Bank Sta=712.9,724.8
XS Rating Curve= 0 ,0
Exp/Cntr=0.3,0.1

Type RM Length L Ch R = 1 ,5429.5  ,190.2,181,171
XS GIS Cut Line= 2
     2304757.321      353764.169     2304550.561      352802.286
#Sta/Elev= 30
       0  856.15    60.9855.5353      96  855.47   115.7853.6332     128  850.86
   143.6 849.757     236  848.22   515.9  850.11   543.9  851.02   559.9  854.01
   563.9  853.89   575.9   849.3   583.9  848.67   611.9  848.91   631.9  853.81
   647.9  851.36  657.31851.2501   687.4 848.785  717.48849.2227   747.9     850
   767.9  854.01   775.9  851.77   783.9  846.09   787.9  844.44   791.9  844.37
   799.8  846.48   811.9  852.94  832.64855.9273  877.33861.5671   983.8  860.46
#Mann= 11 ,-1 , 0
       0     .06       0    60.9     .12       0   115.7    .016       0
   143.6     .06       0  657.31     .04       0   687.4     .06       0
  717.48    .016       0   783.9    .045       0   799.8     .12       0
  832.64    .016       0  877.33     .12       0
#XS Ineff= 2 , 0
          765.62  854.25
Permanent Ineff=
       F       F
Bank Sta=783.9,799.8
XS Rating Curve= 0 ,0
Exp/Cntr=0.3,0.1

Type RM Length L Ch R = 1 ,5248.5  ,225.7,211.2,198.7
XS GIS Cut Line= 3
     2304975.239      353783.673     2304776.281      352961.625
     2304681.225      352779.819
#Sta/Elev= 30
       0  853.68    63.8   855.5  120.05854.2903  140.03853.6629  170.28851.5126
   183.5  847.58   199.5  845.82   263.3  844.68   554.6   846.6   566.5  847.02
   586.5  850.17   606.4  847.44  656.26847.7406   678.2  847.53  690.92845.2885
   706.2  842.52   726.1   842.6  745.09844.7468     778  843.98  830.04846.0266
   845.8  851.38   853.7  852.27   873.4  844.72   881.3  843.42   886.5  844.95
   897.1  850.01  919.55 853.623   954.1856.7869     976  858.62  1050.9   857.2
#Mann= 12 ,-1 , 0
       0     .06       0  120.05    .016       0  140.03     .12       0
  170.28     .06       0  656.26    .016       0  690.92     .12       0
  745.09     .06       0  830.04     .12       0   873.4    .045       0
   886.5     .12       0  919.55    .016       0   954.1     .12       0
#XS Ineff= 2 , 0
          855.68  852.71
Permanent Ineff=
       F       F
Bank Sta=873.4,886.5
XS Rating Curve= 0 ,0
Exp/Cntr=0.3,0.1

Type RM Length L Ch R = 1 ,5037.3  ,160.9,153.8,147.2
XS GIS Cut Line= 3
     2305386.697      353184.715     2304944.756      352826.132
     2304813.832      352700.304
#Sta/Elev= 30
       0  880.29    15.9  880.37    23.9  878.24    71.6  874.14    91.5  866.52
   98.03857.2216   103.5  851.34   119.4  847.45  146.91846.5074   175.1  837.94
  202.93 837.429  208.68837.5258  264.25837.9819  288.63838.2957   318.4  842.44
   338.3  843.21   366.1   836.9  380.97836.1608     398  835.67  425.44836.5963
  545.66841.0618   565.1  848.42   573.1   848.3   588.8   843.1   596.8   841.2
   604.6  842.21   616.5  846.83  643.06848.2653  684.07849.7692   750.7  852.19
#Mann= 14 ,-1 , 0
       0     .12       0   98.03    .016       0  146.91     .06       0
  202.93     .12       0  208.68     .06       0  264.25     .12       0
  288.63     .06       0  380.97    .016       0  425.44     .06       0
  545.66     .12       0   588.8    .045       0   604.6     .12       0
  643.06    .016       0  684.07     .12       0
#XS Ineff= 2 , 0
          565.91  850.64
Permanent Ineff=
       F       F
Bank Sta=588.8,604.6
XS Rating Curve= 0 ,0
Exp/Cntr=0.3,0.1

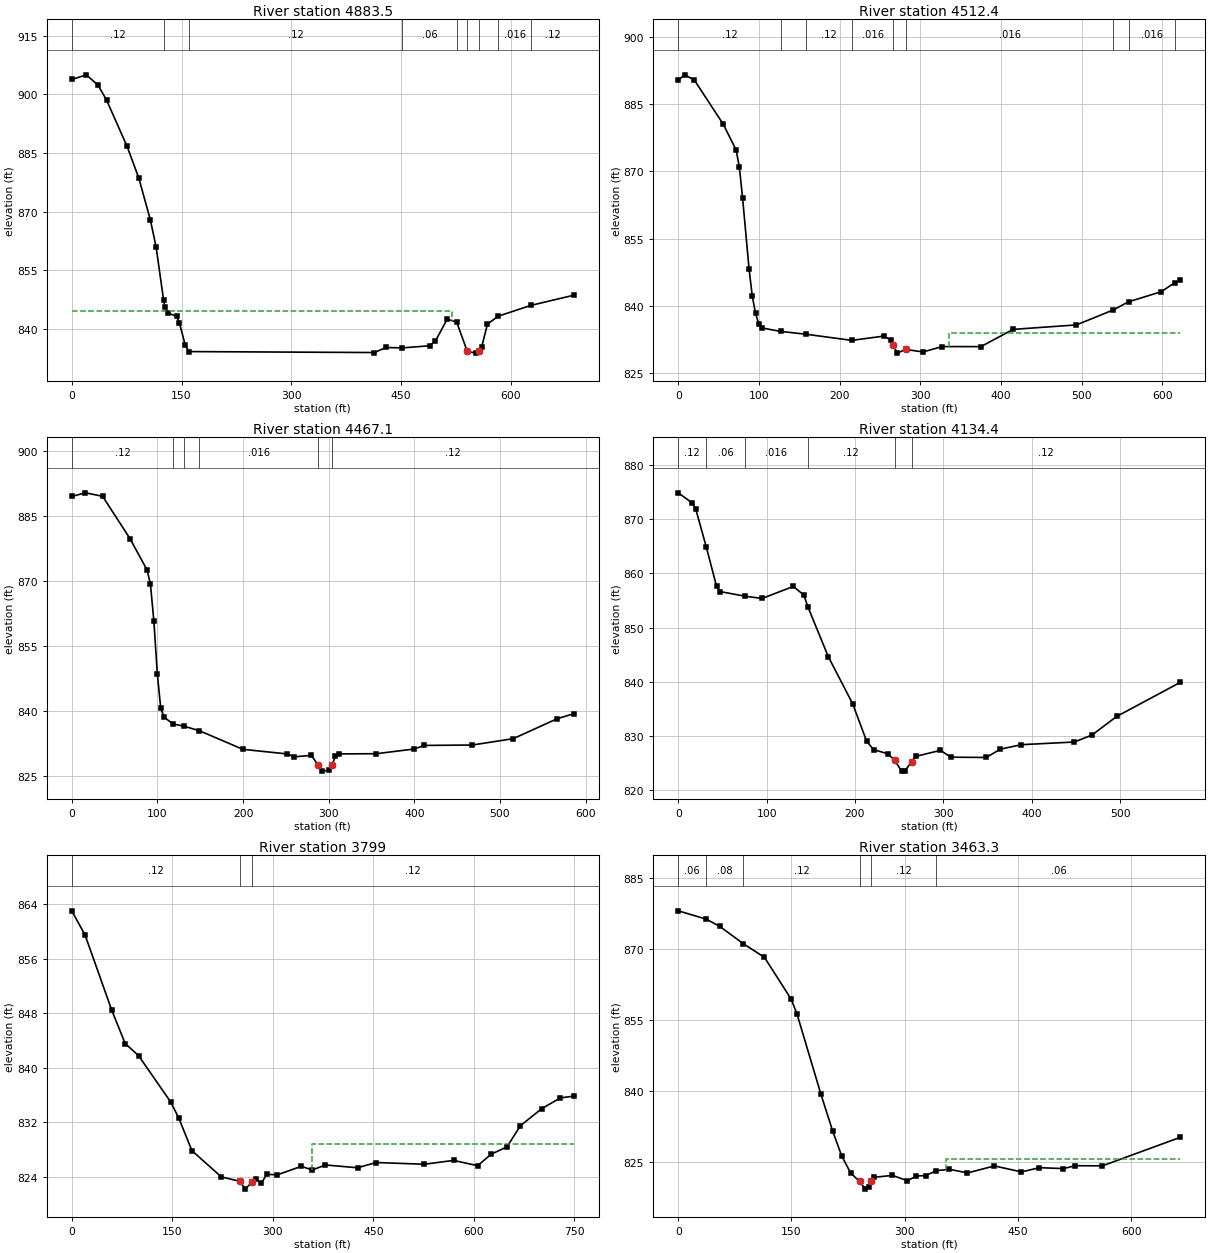
Type RM Length L Ch R = 1 ,4883.5  ,408.6,371.1,194.6
XS GIS Cut Line= 3
     2305518.902      352878.291     2305038.433      352698.603
     2304894.406      352602.367
#Sta/Elev= 30
       0  903.77    19.9  904.96    35.8  902.34    47.7  898.45    75.6  886.67
    91.5  878.65   107.4  867.91   115.3  860.95  125.46847.4268   127.2  845.66
   131.2  844.08   143.2  843.29   147.1  841.59   155.1  835.87  160.01834.2454
   413.6     834   429.5  835.29  451.76835.1902   489.1  835.73   497.1  836.99
     513   842.5  526.02 841.812   540.5  834.32   552.3  833.85   556.3  834.35
   560.2  835.41   568.1  841.26  582.75843.2823  627.67846.0571   686.2  848.65
#Mann= 9 ,-1 , 0
       0     .12       0  125.46    .016       0  160.01     .12       0
  451.76     .06       0  526.02     .12       0   540.5    .045       0
   556.3     .12       0  582.75    .016       0  627.67     .12       0
#XS Ineff= 2 , 0
          520.03  844.57
Permanent Ineff=
       F       F
Bank Sta=540.5,556.3
XS Rating Curve= 0 ,0
Exp/Cntr=0.3,0.1

Type RM Length L Ch R = 1 ,4512.4  ,44.9,45.3,177.7
XS GIS Cut Line= 4
     2305528.852      352351.119     2305090.082      352498.951
     2305009.787      352535.843     2304939.861      352523.146
#Sta/Elev= 30
       0  890.33       8  891.52      20  890.35    55.9  880.48    71.8  874.75
    75.8  870.91    79.8  864.01    87.8  848.27    91.8  842.16    95.8  838.36
    99.8  836.01   103.8  835.09  127.02  834.32  158.61833.6854  215.21832.3215
   255.4  833.29   263.4  832.34   266.8  831.25   271.4  829.48   281.8   830.3
   303.4  829.75   327.3  830.94   375.2  830.93   415.1  834.77   493.7  835.77
  539.54839.1243  558.21840.9228   598.8  843.17   615.7 845.218   622.4  845.71
#Mann= 9 ,-1 , 0
       0     .12       0  127.02    .016       0  158.61     .12       0
  215.21    .016       0   266.8    .045       0   281.8    .016       0
  539.54     .12       0  558.21    .016       0   615.7     .12       0
#XS Ineff= 2 , 0
                          336.08          833.86
Permanent Ineff=
       F       F
Bank Sta=266.8,281.8
XS Rating Curve= 0 ,0
Exp/Cntr=0.3,0.1

Type RM Length L Ch R = 1 ,4467.1  ,326.5,332.7,340.5
XS GIS Cut Line= 3
     2305548.987      352299.325     2305052.025      352464.255
     2304989.589      352458.579
#Sta/Elev= 30
       0  889.47      16   890.3      36   889.5      68  879.73    87.9  872.52
    91.9  869.19    95.9  860.62    99.9  848.55   103.9  840.58   107.9  838.52
  118.35836.9808     131836.4738  148.84835.4336   199.8  831.13   251.8  830.06
   259.8   829.4   279.8  829.74   287.8  827.46   291.7   826.1   299.8  826.27
   303.8  827.43   307.8  829.51   311.8  830.07   355.7  830.12   399.7   831.2
   411.7  832.03   467.7  832.12   515.6  833.59   566.7  838.18   586.3  839.35
#Mann= 6 ,-1 , 0
       0     .12       0  118.35    .016       0     131     .08       0
  148.84    .016       0   287.8    .045       0   303.8     .12       0
Bank Sta=287.8,303.8
XS Rating Curve= 0 ,0
Exp/Cntr=0.3,0.1

Type RM Length L Ch R = 1 ,4134.4  ,314.3,335.3,353.9
XS GIS Cut Line= 3
     2305482.128      352029.274     2305231.806       352085.99
     2304924.451      352136.358
#Sta/Elev= 30
       0  874.87    15.8  873.01    19.7  871.94   31.86864.8167    43.4   857.6
    47.4  856.66   75.35855.8113    94.8  855.39   130.3  857.61   142.2     856
  146.54 853.908   169.8  844.65   197.4  835.96   213.2  829.05   221.1  827.51
   236.9  826.76   244.8  825.58   252.7  823.55   256.7  823.62   264.2  825.32
   268.6  826.26   296.6  827.38   308.6  826.12   348.5  826.07   364.5   827.6
   388.4  828.43   448.3  828.92   468.3  830.22   496.2  833.64   568.1  839.92
#Mann= 6 ,-1 , 0
       0     .12       0   31.86     .06       0   75.35    .016       0
  146.54     .12       0   244.8    .045       0   264.2     .12       0
Bank Sta=244.8,264.2
XS Rating Curve= 0 ,0
Exp/Cntr=0.3,0.1

Type RM Length L Ch R = 1 ,3799    ,332.3,335.7,334.1
XS GIS Cut Line= 2
     2305501.278      351870.246     2304785.098      351650.453
#Sta/Elev= 30
       0  863.06    19.9  859.49    59.8  848.42    79.7  843.56    99.6  841.78
   147.4     835   159.4  832.67   179.3  827.81   223.2  823.96     251   823.3
     259  822.16   268.5  823.18     275  823.67   282.9  823.01   290.9  824.34
   306.8  824.26   342.7  825.52   358.6  824.97   378.6  825.71   426.4   825.3
   454.3  826.07     526  825.82   569.8  826.38   605.7   825.6   625.6  827.28
   649.5  828.38   669.4  831.47   701.3  833.99   729.2  835.57   749.2  835.83
#Mann= 3 ,-1 , 0
       0     .12       0     251    .045       0   268.5     .12       0
#XS Ineff= 2 , 0
                          357.95          828.85
Permanent Ineff=
       F       F
Bank Sta=251,268.5
XS Rating Curve= 0 ,0
Exp/Cntr=0.3,0.1

Type RM Length L Ch R = 1 ,3463.3  ,335.9,321.6,307.8
XS GIS Cut Line= 3
      2305589.36      351660.365     2305360.947      351553.772
     2304984.255      351383.977
#Sta/Elev= 30
       0  877.98   37.01876.2372    55.1  874.69   86.36871.0339   114.2  868.18
   149.7  859.34   157.5  856.15     189  839.34   204.8  831.46   216.6  826.29
   228.4  822.73   240.2  820.92   248.1  819.31   252.1  819.74     256  821.03
     260  821.82   283.8   822.2   303.7  821.09   315.6  822.08   327.6  822.17
  341.99823.1902   359.3  823.49   383.2  822.72   418.9   824.2   454.7  822.94
   478.5  823.83   510.3  823.64   526.2  824.25     562  824.22   665.2  830.23
#Mann= 6 ,-1 , 0
       0     .06       0   37.01     .08       0   86.36     .12       0
   240.2    .045       0     256     .12       0  341.99     .06       0
#XS Ineff= 2 , 0
                          354.97          825.61
Permanent Ineff=
       F       F
Bank Sta=240.2,256
XS Rating Curve= 0 ,0
Exp/Cntr=0.3,0.1

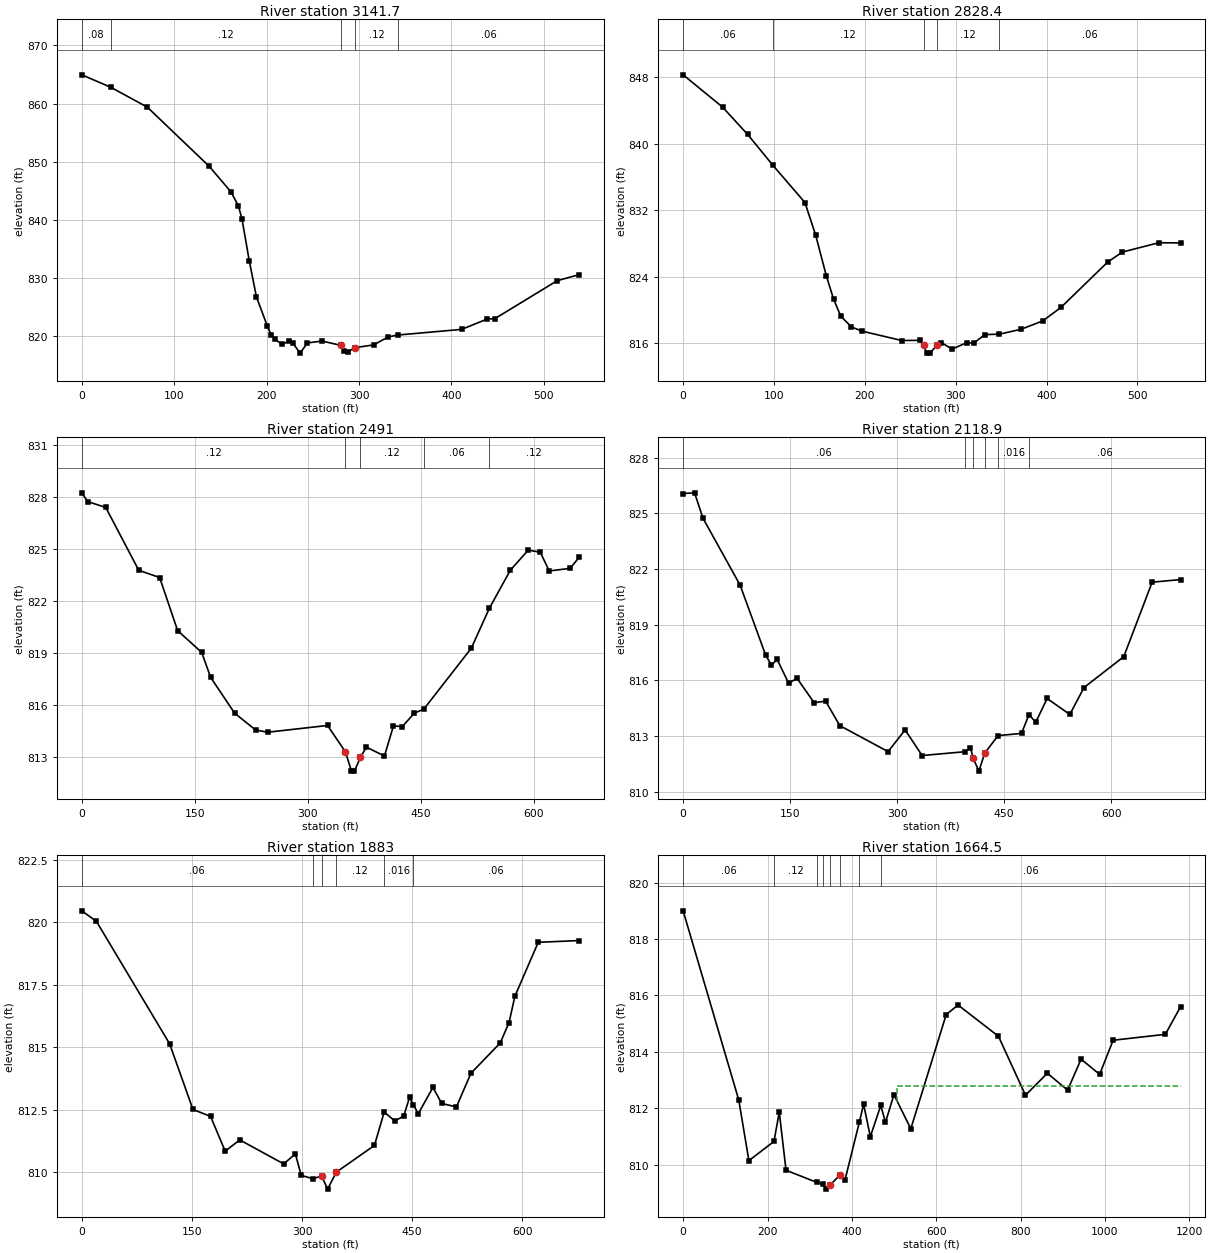
Type RM Length L Ch R = 1 ,3141.7  ,316.2,313.3,313.9
XS GIS Cut Line= 3
     2305683.785       351251.84      2305448.64      351275.134
     2305147.656      351250.772
#Sta/Elev= 30
       0  864.96   31.28862.8264    70.9  859.41   137.8  849.25   161.5  844.84
   169.4  842.45   173.3  840.25   181.2  833.03     189  826.81   200.8  821.78
   204.8  820.34   208.7  819.54   216.6  818.67   224.5  819.18   228.4  818.86
   236.3  817.14   244.2   818.9   260.1  819.21     280  818.49     284  817.53
     288  817.39   295.9  818.09   315.8  818.55   331.6  819.92  341.88820.2499
   411.1  821.22   438.9  823.01   446.9  823.05   514.4  829.58   538.3  830.63
#Mann= 5 ,-1 , 0
       0     .08       0   31.28     .12       0     280    .045       0
   295.9     .12       0  341.88     .06       0
Bank Sta=280,295.9
XS Rating Curve= 0 ,0
Exp/Cntr=0.3,0.1

Type RM Length L Ch R = 1 ,2828.4  ,345.9,337.4,310.5
XS GIS Cut Line= 3
     2305699.208      350988.463     2305427.121      350991.069
     2305153.075       350964.07
#Sta/Elev= 30
       0  848.31    43.4  844.42      71  841.13   98.95837.3898   134.1  832.92
   145.9  828.99   157.7  824.06   165.6  821.29   173.5  819.24   185.3  817.93
   197.2  817.42   240.6   816.3   260.3  816.32   264.6   815.7   268.2  814.78
   272.1  814.85   279.6  815.73   284.1  816.06     296  815.26     312  816.04
     320  815.99     332  817.01  348.18 817.067   371.9  817.65   395.8  818.66
   415.8  820.28   467.6  825.78   483.6  826.96   523.5  828.08   547.5  828.06
#Mann= 5 ,-1 , 0
       0     .06       0   98.95     .12       0   264.6    .045       0
   279.6     .12       0  348.18     .06       0
Bank Sta=264.6,279.6
XS Rating Curve= 0 ,0
Exp/Cntr=0.3,0.1

Type RM Length L Ch R = 1 ,2491    ,344.5,372.1,389.6
XS GIS Cut Line= 2
     2305723.097      350616.352     2305088.837      350800.607
#Sta/Elev= 30
       0  828.23       8  827.72    31.8  827.39    75.6  823.77   103.4  823.35
   127.3  820.29   159.2  819.04   171.1   817.6   202.9  815.54   230.8  814.57
   246.7  814.44   326.3  814.83   350.1  813.31   358.1   812.2   362.1   812.2
     370     813     378  813.58   401.9  813.07   413.8   814.8   425.7  814.77
   441.6  815.54  454.15815.7703   517.2  819.28  541.28821.5862     569  823.77
   592.8  824.93   608.8  824.81   620.7  823.73   648.5  823.88   660.5  824.52
#Mann= 5 ,-1 , 0
       0     .12       0   350.1    .045       0     370     .12       0
  454.15     .06       0  541.28     .12       0
Bank Sta=350.1,370
XS Rating Curve= 0 ,0
Exp/Cntr=0.3,0.1

Type RM Length L Ch R = 1 ,2118.9  ,238.4,235.9,240.9
XS GIS Cut Line= 3
     2305730.675      350568.401     2305533.796      350535.002
     2305102.645      350286.659
#Sta/Elev= 30
       0  826.06      16   826.1      28  824.72    79.9  821.13   115.8  817.35
   123.8  816.83   131.8  817.13   147.8  815.86   159.8  816.11   183.7   814.8
   199.7  814.89   219.6  813.57   287.3  812.17   311.1  813.34     335  811.96
  394.58812.1632   402.7  812.38   406.7   811.8   414.6  811.12   422.6  812.08
  441.38813.0313   474.3  813.15  484.82 814.164   494.2  813.75   510.2  815.03
     542  814.17   561.9  815.62   617.6  817.28   657.4  821.29   697.2  821.43
#Mann= 6 ,-1 , 0
       0     .06       0  394.58     .12       0   406.7    .045       0
   422.6     .12       0  441.38    .016       0  484.82     .06       0
Bank Sta=406.7,422.6
XS Rating Curve= 0 ,0
Exp/Cntr=0.3,0.1

Type RM Length L Ch R = 1 ,1883    ,205.5,218.5,220.2
XS GIS Cut Line= 2
     2305789.289      350390.585     2305180.251      350093.707
#Sta/Elev= 30
       0  820.46    19.9  820.04   119.6  815.14   151.4  812.51   175.4  812.23
   195.3  810.84   215.2  811.29     275  810.33   290.9  810.73   298.9  809.87
  314.58809.7392   326.8  809.84   334.8  809.32   346.7     810   398.6  811.07
  411.88812.4028   426.4  812.05   438.4  812.24   446.4  812.99  451.57812.7018
   458.3  812.34   478.3  813.39   490.2  812.75   510.2  812.61   530.1  813.96
   569.9  815.17   581.9  815.98   589.9  817.04   621.7   819.2   677.5  819.27
#Mann= 6 ,-1 , 0
       0     .06       0  314.58     .12       0   326.8    .045       0
   346.7     .12       0  411.88    .016       0  451.57     .06       0
Bank Sta=326.8,346.7
XS Rating Curve= 0 ,0
Exp/Cntr=0.3,0.1

Type RM Length L Ch R = 1 ,1664.5  ,253.8,279,298.7
XS GIS Cut Line= 3
     2305847.065      350309.353     2305338.918      349907.831
     2304852.807      349692.988
#Sta/Elev= 30
       0     819   131.9  812.29   155.9  810.14  215.33810.8229   227.9  811.86
   243.9   809.8  317.39809.3655  331.17809.2974   339.8  809.13   347.8  809.27
   371.8  809.63   383.8  809.46  417.94811.5177   427.8  812.14   443.8  810.99
  468.46812.0964   479.7   811.5   499.7  812.48   539.7  811.27   623.6  815.32
   651.6  815.66   747.5  814.55   811.5  812.46   863.4  813.24   911.4  812.64
   943.3  813.74   987.3   813.2  1019.3  814.41  1143.1  814.62  1179.1   815.6
#Mann= 8 ,-1 , 0
       0     .06       0  215.33     .12       0  317.39     .06       0
  331.17     .12       0   347.8    .045       0   371.8     .12       0
  417.94    .016       0  468.46     .06       0
#XS Ineff= 2 , 0
                          507.95          812.77
Permanent Ineff=
       F       F
Bank Sta=347.8,371.8
XS Rating Curve= 0 ,0
Exp/Cntr=0.3,0.1

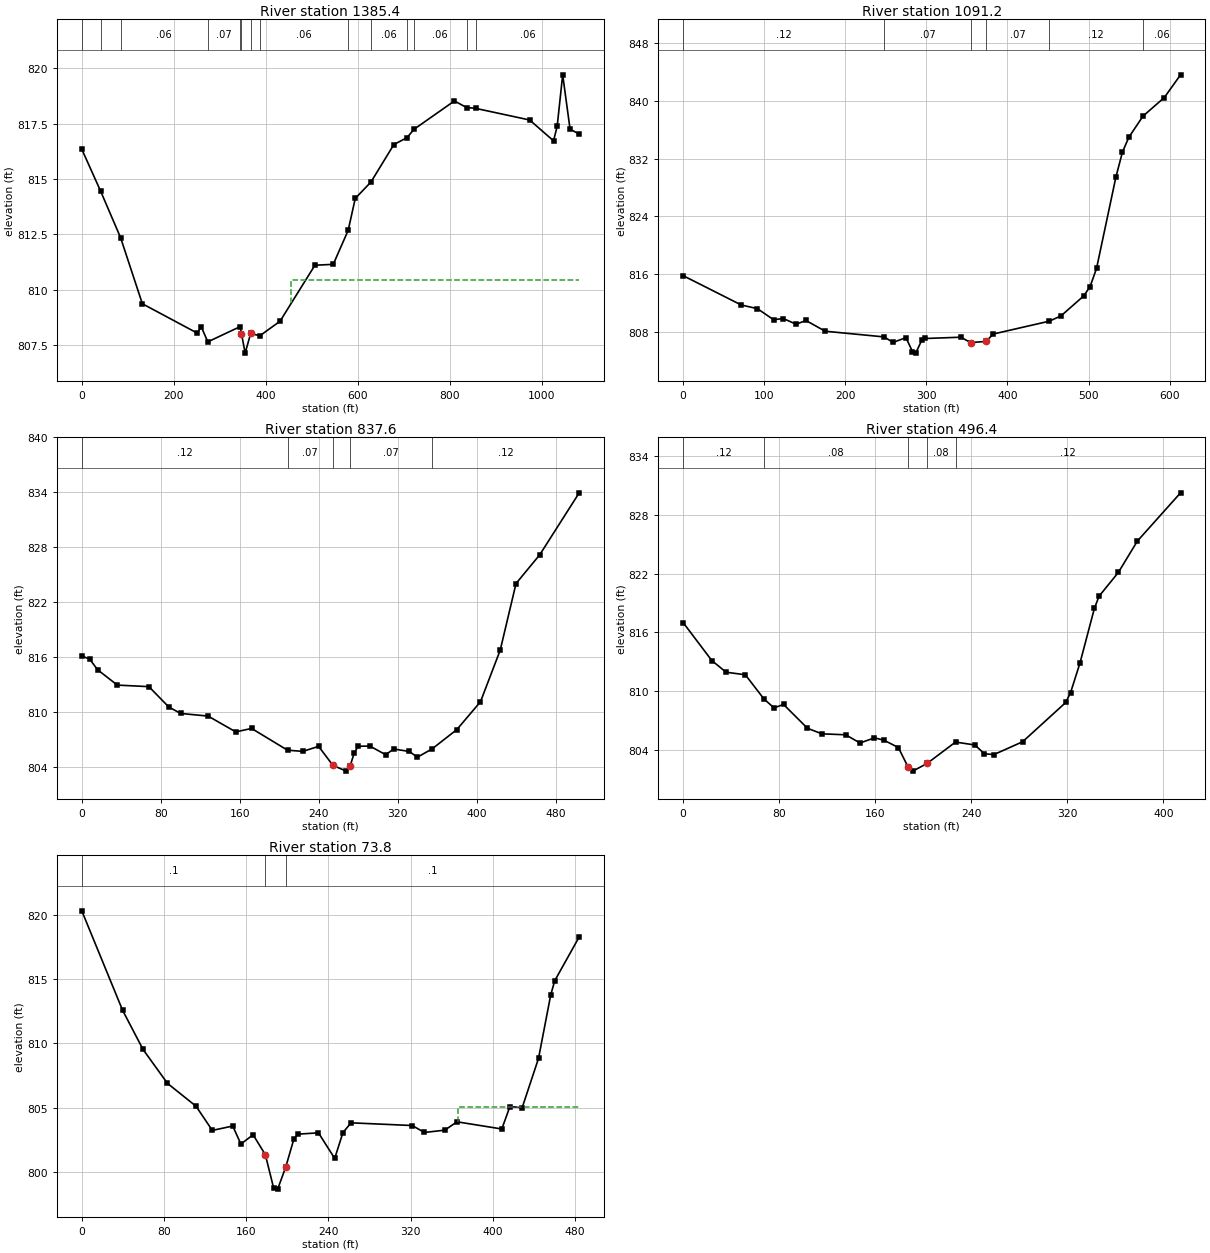
Type RM Length L Ch R = 1 ,1385.4  ,293,294.2,330.2
XS GIS Cut Line= 2
     2305909.095      350229.973     2305385.396      349284.405
#Sta/Elev= 30
       0  816.35    40.9814.4575   84.37812.3516   131.6  809.37   251.3  808.04
   259.3  808.34  273.88807.6495  343.85 808.335     347  808.02     355  807.14
     367  808.03  386.79807.9219   430.8  808.58   506.6  811.11   546.4  811.15
  578.85812.6846   594.3  814.13  628.28814.8656   678.1  816.56  706.88816.8752
  721.95817.2512   809.7  818.53  836.09818.2342  855.67818.1962   973.2  817.67
  1025.1  816.73    1033  817.38    1045  819.71    1061  817.26  1080.9  817.03
#Mann= 14 ,-1 , 0
       0     .06       0    40.9     .12       0   84.37     .06       0
  273.88     .07       0  343.85     .12       0     347    .045       0
     367     .12       0  386.79     .06       0  578.85    .016       0
  628.28     .06       0  706.88     .08       0  721.95     .06       0
  836.09     .08       0  855.67     .06       0
#XS Ineff= 2 , 0
                          455.11          810.44
Permanent Ineff=
       F       F
Bank Sta=347,367
XS Rating Curve= 0 ,0
Exp/Cntr=0.3,0.1

Type RM Length L Ch R = 1 ,1091.2  ,242.6,253.6,264.5
XS GIS Cut Line= 2
     2305956.419      350191.684     2305922.396       349579.28
#Sta/Elev= 30
       0  815.78    71.7  811.71    91.6   811.2   111.5  809.67   123.5  809.83
   139.4  809.04   151.4  809.56   175.2  808.07  247.75 807.282   258.9  806.52
   274.8  807.18   282.8  805.25   286.8  805.03   294.7  806.92   298.7  807.06
   342.5  807.24   354.5  806.49   373.6  806.66   382.4  807.68  451.53 809.463
     466   810.2   493.9  812.96   501.8  814.25   509.8  816.78   533.7  829.47
   541.7  832.91   549.6  834.98   567.1  837.92   593.4   840.5   613.4  843.65
#Mann= 6 ,-1 , 0
       0     .12       0  247.75     .07       0   354.5    .045       0
   373.6     .07       0  451.53     .12       0   567.1     .06       0
Bank Sta=354.5,373.6
XS Rating Curve= 0 ,0
Exp/Cntr=0.3,0.1

Type RM Length L Ch R = 1 ,837.6   ,325,341.2,304.2
XS GIS Cut Line= 2
     2306082.842      350166.078     2306228.498      349683.709
#Sta/Elev= 30
       0   816.1       8  815.75      16  814.59      36  812.91      68  812.74
      88  810.53     100  809.81     128  809.52     156  807.79     172  808.17
  208.42805.7885     224  805.66   239.9  806.21   254.4  804.13   267.9   803.5
   271.9  804.08   275.9  805.46   279.9  806.22   291.9  806.24   307.9  805.29
   315.9  805.92   331.9  805.65   339.9  805.02  354.95805.9364   379.9  808.04
   403.9  811.09   423.9  816.74   439.9  824.02   463.9  827.16   503.9  833.94
#Mann= 5 ,-1 , 0
       0     .12       0  208.42     .07       0   254.4    .045       0
   271.9     .07       0  354.95     .12       0
Bank Sta=254.4,271.9
XS Rating Curve= 0 ,0
Exp/Cntr=0.3,0.1

Type RM Length L Ch R = 1 ,496.4   ,391.2,422.6,431.1
XS GIS Cut Line= 2
     2306448.122      350111.477     2306390.449      349701.361
#Sta/Elev= 30
       0  817.01    23.9  813.13    35.8  811.94    51.8  811.68   67.34809.2032
    75.7   808.3    83.6  808.65   103.5  806.22   115.5  805.65   135.4  805.55
   147.3  804.71   159.3  805.24   167.2     805   179.2  804.25   187.2  802.29
   191.2  801.84   203.1  802.62  226.82804.8092   242.9  804.51   250.9  803.61
   258.8  803.53   282.7  804.84   318.6  808.85   322.6  809.85   330.5   812.9
   342.5  818.48   346.4  819.71   362.4  822.13   378.3  825.34   414.2  830.26
#Mann= 5 ,-1 , 0
       0     .12       0   67.34     .08       0   187.2    .045       0
   203.1     .08       0  226.82     .12       0
Bank Sta=187.2,203.1
XS Rating Curve= 0 ,0
Exp/Cntr=0.3,0.1

Type RM Length L Ch R = 1 ,73.8    ,84.1,73.8,63.4
XS GIS Cut Line= 3
     2306629.474      350166.563     2306753.756      349917.999
     2306710.949      349716.365
#Sta/Elev= 30
       0  820.31    39.7  812.57    59.6  809.52    83.4  806.88   111.2   805.1
     127  803.22   146.9  803.56   154.8  802.16   166.7  802.88   178.6  801.33
   186.6  798.76   190.6  798.65   198.5  800.38   206.4  802.56   210.4  802.93
   230.3  803.03   246.1  801.04   254.1  803.05     262  803.81   321.5   803.6
   333.4  803.06   353.2  803.24   365.1  803.89   408.7  803.33   416.6  805.08
   428.5  804.99   444.4  808.82   456.3  813.77   460.2  814.87     484  818.28
#Mann= 3 , 0 , 0
       0      .1       0   178.6    .045       0   198.5      .1       0
#XS Ineff= 2 , 0
                          365.77          805.01
Permanent Ineff=
       F       F
Bank Sta=178.6,198.5
XS Rating Curve= 0 ,0
Exp/Cntr=0.3,0.1

Chan Stop Cuts=-1
Use User Specified Reach Order=0
Composite Channel Slope=5